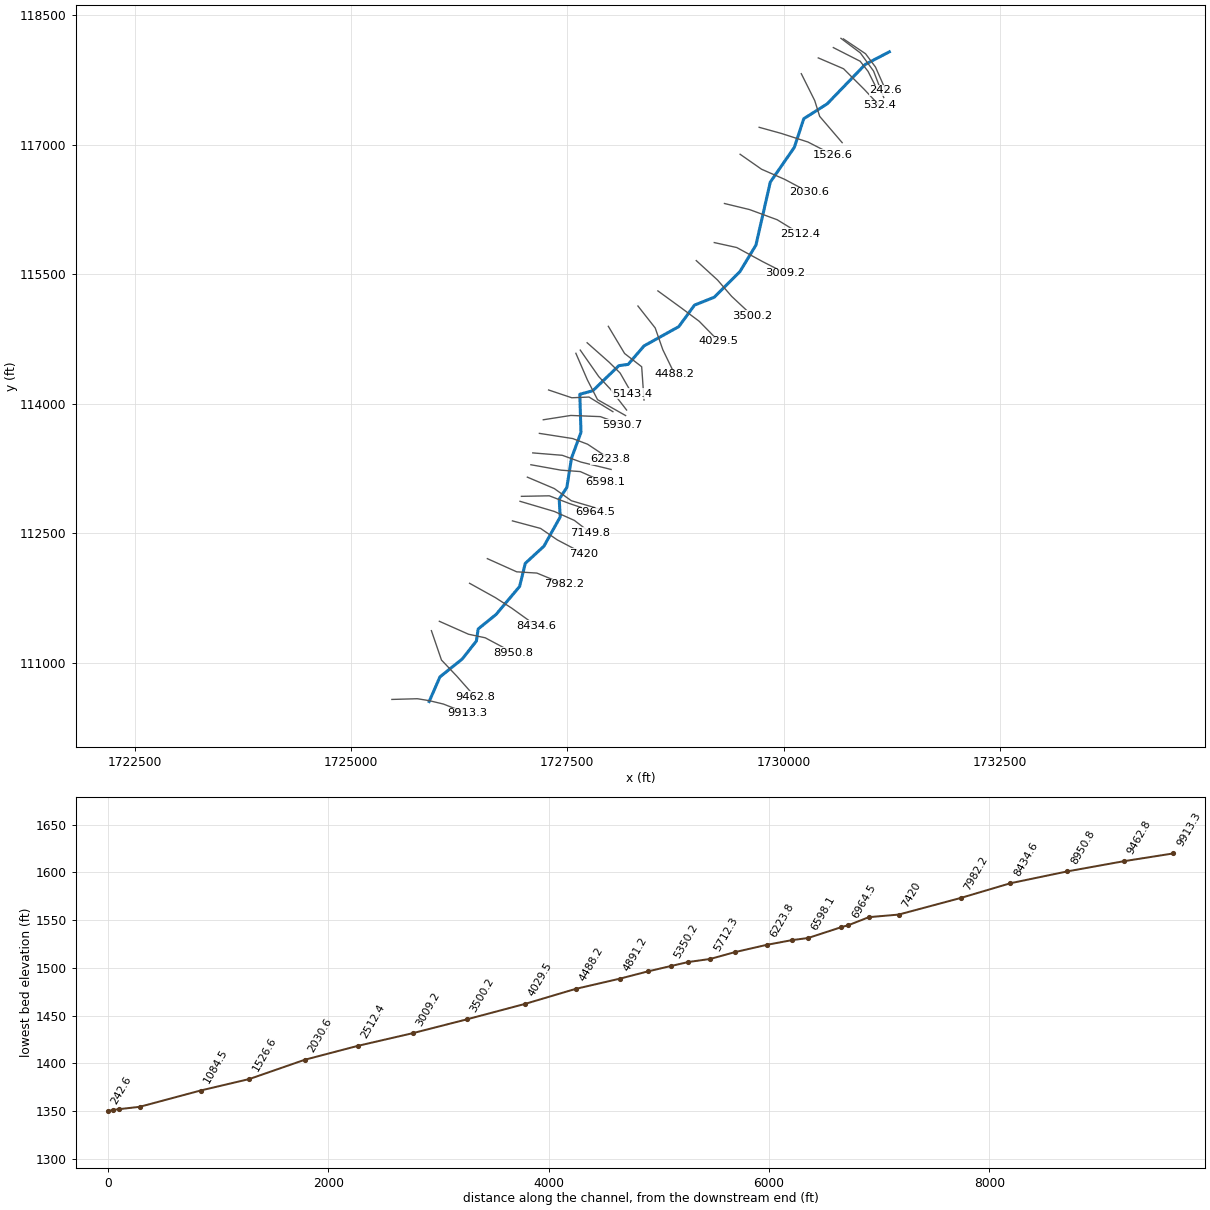
--- Middle Fork Bradshaw Creek.prj (project) ---

Proj Title=Middle Fork Bradshaw Creek
Current Plan=p01
Default Exp/Contr=0,0
English Units
Geom File=g01
Flow File=f01
Plan File=p01
BEGIN DESCRIPTION:
END DESCRIPTION:
DSS Export Rating Curves= 0
DSS Export Rating Curve Sorted= 0
DSS Export Volume Flow Curves= 0
DXF OffsetX= 0
DXF OffsetY= 0
DXF ScaleX= 0
DXF ScaleY= 0

--- Middle Fork Bradshaw Creek.p01 (plan) ---

Plan Title=Floodplain
Program Version=4.00
Geom File=g01
Flow File=f01
K Sum by GR=0
Std Step Tol=0.01
Critical Tol=0.01
Num of Std Step Trials=20
Max Error Tol=0.3
Flow Tol Ratio=0.001
Split Flow NTrial=30
Split Flow Tol=0.02
Split Flow Ratio=0.02
Log Output Level=0
Friction Slope Method=1
Unsteady Friction Slope Method=2
Unsteady Bridges Friction Slope Method=1
Global Log Level=0
CheckData=False
Run HTab=0
Run UNet=0
Run PostProcess=0
UNET Theta=0
UNET Theta Warmup=0
UNET ZTol=0
UNET ZSATol=0
UNET MxIter=0
UNET MaxInSteps=0
UNET DtIC=0
UNET DtMin=0
UNET MaxCRTS=0
UNET WFStab=0
UNET SFStab=0
UNET WFX=0
UNET SFX=0
UNET DSS MLevel=0
UNET DZMax Abort=0
UNET Convert EG Bridges=0
UNET Use Existing IB Tables=0
UNET Froude Limit=0
UNET Froude Power=0
Write IC File=0
Echo Input=False
Echo Output=False
Write Detailed=0

--- Middle Fork Bradshaw Creek.f01 (steady flow) ---

Flow Title=NFF Regression Equation
Program Version=4.00
Number of Profiles=1
Profile Names=P100yr
River Rch & RM=Middle Fork B...,Main      ,9913.3
838.6443
River Rch & RM=Middle Fork B...,Main      ,9462.8
848.7482
River Rch & RM=Middle Fork B...,Main      ,6223.8
933.6061
River Rch & RM=Middle Fork B...,Main      ,5930.7
1115.795
River Rch & RM=Middle Fork B...,Main      ,286.8
1237.471
Boundary for River Rch & Prof#=Middle Fork B...,Main      ,1
Up Type=0
Dn Type=3
Dn Slope=0.03558

--- Middle Fork Bradshaw Creek.g01 (geometry) ---

Geom Title=USGS 10m DEM
Program Version=4.00

River Reach=Middle Fork B...,Main
Reach XY= 30
     1725903.548      110553.764     1726027.836      110838.526
     1726285.325      111045.623     1726449.404      111254.563
     1726469.647      111393.967     1726677.346      111562.858
     1726948.707      111886.353     1727014.208      112153.705
     1727229.859      112352.882      1727418.52      112692.566
     1727406.229      112897.205     1727494.481      113032.498
     1727548.186      113371.623     1727658.174      113671.434
     1727644.667      114112.133     1727795.278      114153.731
     1728095.118      114443.365      1728203.22       114458.54
     1728387.059      114672.766      1728788.31       114895.66
     1728970.483      115145.279     1729198.383      115236.439
     1729495.021      115532.929     1729680.012      115839.615
     1729845.918      116569.028     1730124.301      116972.776
      1730233.05      117304.252     1730503.491      117475.937
     1730944.085      117933.287     1731222.095      118078.672

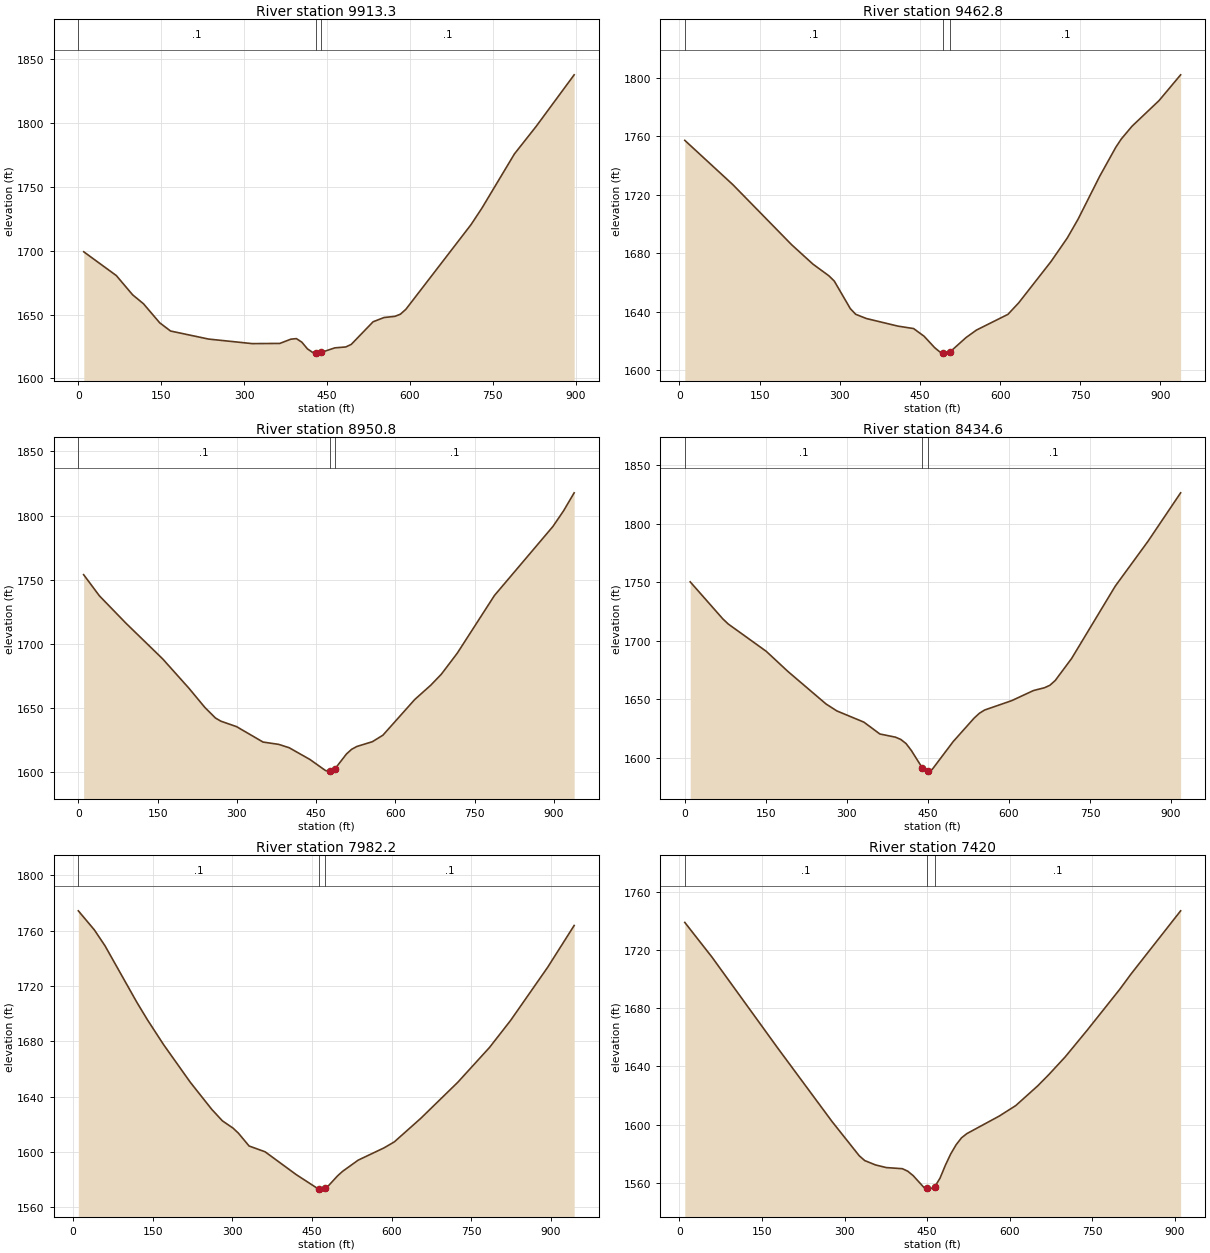
Type RM Length L Ch R = 1 ,9913.3  ,463.6,450.6,439
XS GIS Cut Line= 5
     1725472.398      110577.887     1725767.048      110586.116
     1725905.155      110563.634     1726068.559      110524.219
     1726342.863       110416.43
#Sta/Elev= 30
     9.8 1699.17    68.8 1680.54    98.3 1665.46   117.9 1658.48   147.4  1643.5
     167  1637.1   235.8  1630.8   314.8 1627.24   364.7 1627.39   384.7 1630.72
   394.7 1631.16   404.7 1628.33   414.7 1623.12   424.7 1620.19   429.7 1619.99
   434.7 1619.79   439.7 1620.38   464.4 1623.92   484.1 1624.62     494 1626.62
   533.6 1644.36   553.3 1647.67   573.1  1648.6     583 1650.29   592.9 1654.12
   710.8 1720.43   730.5 1733.33   789.4 1775.83   828.7 1797.38   897.5 1837.78
#Mann= 3 , 0 , 0
       0      .1       0   429.7    .045       0   439.7      .1       0
Bank Sta=429.7,439.7
XS Rating Curve= 0 ,0
Exp/Cntr=0.3,0.1

Type RM Length L Ch R = 1 ,9462.8  ,499.4,512,524.5
XS GIS Cut Line= 4
     1725929.224      111374.566     1726045.688       111034.18
     1726221.185      110849.323      1726435.06      110607.007
#Sta/Elev= 30
      10 1757.05    99.9 1726.79   209.9 1685.73   249.8 1672.46   279.8 1664.44
   289.8 1660.85   319.8 1642.01   329.8 1638.18   349.8 1635.27   408.8 1630.09
   438.2  1628.4   457.8 1623.17   477.4 1615.43   487.2 1612.45   493.9 1611.88
     497 1611.62   506.8 1612.59   536.2 1622.23   555.8 1627.37   614.7 1638.11
   634.9    1646   695.5  1674.3   725.8 1690.33     746 1703.18   786.4 1732.47
   816.7  1752.4   826.8 1757.95     847 1766.73   897.5 1784.23   937.9 1801.84
#Mann= 3 , 0 , 0
      10      .1       0   493.9    .045       0   506.8      .1       0
Bank Sta=493.9,506.8
XS Rating Curve= 0 ,0
Exp/Cntr=0.3,0.1

Type RM Length L Ch R = 1 ,8950.8  ,523.6,516.1,508.7
XS GIS Cut Line= 4
     1726021.112      111482.998     1726358.715      111332.972
     1726551.289      111291.952     1726879.407       111116.81
#Sta/Elev= 30
      10    1754    39.9 1737.51    89.9 1716.28   159.8 1688.32   209.7 1665.36
   239.6 1650.51   259.6 1642.32   269.6 1639.91   299.5 1635.62   349.5 1623.63
   379.3 1621.81     399  1619.2   438.3 1610.05   467.9  1601.4   475.8 1601.06
   477.7 1600.98   485.8 1602.82   507.3 1614.28   517.1 1617.94     527 1620.17
   556.5 1623.91   576.4 1628.97   636.7  1656.8   666.9 1667.89     687 1676.49
   717.1 1692.84   787.5  1737.8   898.1 1791.54   918.2 1803.68   938.3 1817.74
#Mann= 3 , 0 , 0
       0      .1       0   475.8    .045       0   485.8      .1       0
Bank Sta=475.8,485.8
XS Rating Curve= 0 ,0
Exp/Cntr=0.3,0.1

Type RM Length L Ch R = 1 ,8434.6  ,442.7,452.5,462.2
XS GIS Cut Line= 4
     1726370.576      111923.067     1726669.028      111756.921
     1726856.369      111635.901     1727142.957      111429.882
#Sta/Elev= 30
      10 1750.26    70.3 1718.67    80.4 1714.25   150.7 1690.94   190.9  1673.7
   261.2 1646.02   281.3 1640.04   331.5 1630.42     361 1620.32   390.1 1617.58
   399.8 1615.63   409.5 1612.13   419.2 1606.27   439.2 1591.59   448.2  1588.6
   449.2 1588.75   457.9 1590.09   496.7 1613.84   535.5 1633.92   545.2 1638.02
   554.9 1640.79   604.9 1648.78   645.3 1657.43   665.5 1659.79   675.5 1661.87
   685.6 1666.04   715.9 1684.83   796.6 1746.57   857.1 1784.82   917.6 1826.28
#Mann= 3 , 0 , 0
       0      .1       0   439.2    .045       0   449.2      .1       0
Bank Sta=439.2,449.2
XS Rating Curve= 0 ,0
Exp/Cntr=0.3,0.1

Type RM Length L Ch R = 1 ,7982.2  ,572.7,562.2,551.7
XS GIS Cut Line= 4
     1726575.978      112208.513     1726915.148      112056.035
     1727148.118      112041.543     1727461.217      111912.675
#Sta/Elev= 30
    10.1 1774.22    40.2 1760.49    60.3 1748.99   120.6 1707.93   140.7 1695.22
   170.9 1677.41   221.1 1650.28   261.3 1630.82   281.4 1622.48   301.5 1617.21
   311.6 1613.56   331.7  1604.3   361.8 1600.13   420.5 1583.62   458.4 1574.19
  463.98 1573.55   469.1 1573.14   475.1 1574.16   478.9 1574.64   498.3 1582.72
     508 1586.06   537.2 1594.09   585.8 1602.94   605.3 1607.31   655.1 1624.31
   724.8 1650.36   784.5  1675.5   824.4 1695.13   894.1 1733.48   943.9 1763.62
#Mann= 3 , 0 , 0
    10.1      .1       0  463.98    .045       0   475.1      .1       0
Bank Sta=463.98,475.1
XS Rating Curve= 0 ,0
Exp/Cntr=0.3,0.1

Type RM Length L Ch R = 1 ,7420    ,266.4,270.2,273.9
XS GIS Cut Line= 4
     1726865.979      112646.068     1727191.043      112558.656
     1727384.165      112425.969      1727684.44      112268.089
#Sta/Elev= 30
     9.9 1738.86    59.4 1714.97   178.2 1652.85   277.2 1602.22   326.7 1578.66
   336.6 1575.38   356.1  1572.4   375.7 1570.58     405  1569.8   414.7  1568.1
   424.5 1565.06     444 1556.99     450 1556.25   453.8 1555.78   463.5 1557.25
   473.3 1563.28   483.1 1572.22   492.8 1579.97   502.6 1586.26   512.3 1590.98
   522.1 1593.89   580.9 1605.94   610.8 1613.12   650.7 1626.66   670.7 1634.32
   700.6 1646.54   740.5 1664.85   800.4  1693.3   820.4 1703.58   910.2 1746.82
#Mann= 3 , 0 , 0
     9.9      .1       0     450    .045       0   463.5      .1       0
Bank Sta=450,463.5
XS Rating Curve= 0 ,0
Exp/Cntr=0.3,0.1

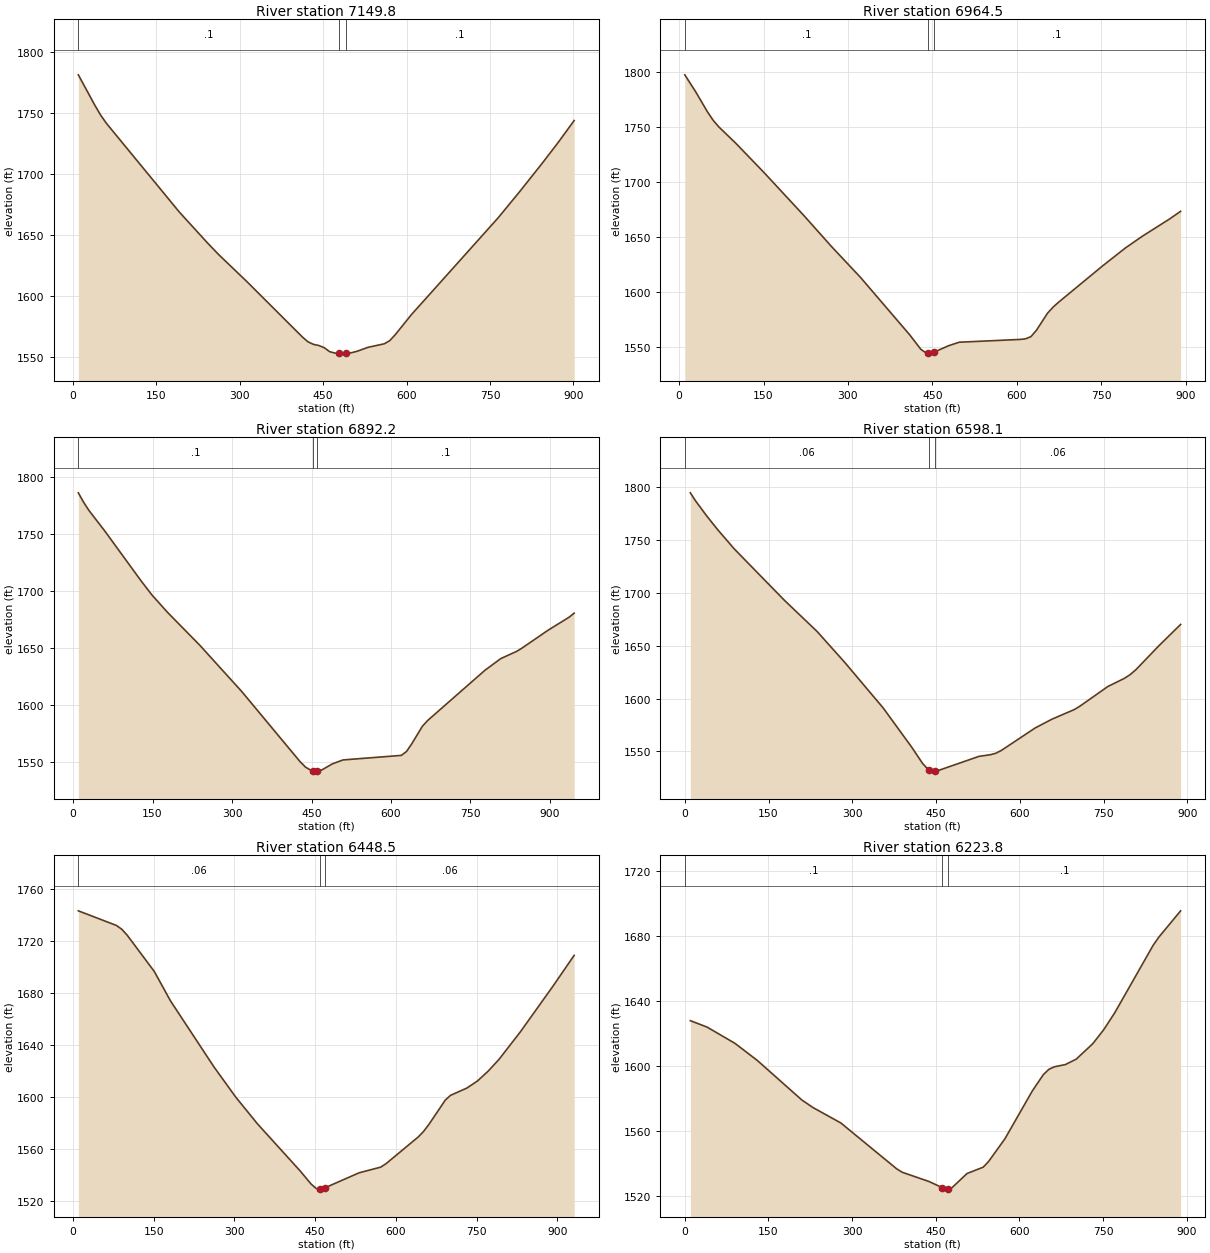
Type RM Length L Ch R = 1 ,7149.8  ,184.1,185.3,186.5
XS GIS Cut Line= 4
     1726953.391      112872.794     1727349.478      112755.334
     1727581.667      112651.531     1727767.418      112509.486
#Sta/Elev= 30
    10.1 1781.12    40.3 1755.79    50.4 1747.98    60.5 1741.43   191.5 1668.76
   241.8 1643.61     262 1633.98   312.4 1611.99   413.1 1566.19   422.9 1562.36
   432.7 1560.27   442.5 1559.32   452.3 1557.49     462 1554.23   471.8  1553.1
  478.86  1553.1  481.66 1553.09   491.4 1553.11   501.2 1553.44     511 1554.58
   530.5 1557.81   559.9 1560.72   569.7 1563.28   579.4 1568.01   608.8 1584.64
   764.9 1664.07   803.9 1685.72   842.9 1708.07   872.1 1725.41   901.3 1743.66
#Mann= 3 , 0 , 0
    10.1      .1       0  478.86    .045       0   491.4      .1       0
Bank Sta=478.86,491.4
XS Rating Curve= 0 ,0
Exp/Cntr=0.3,0.1

Type RM Length L Ch R = 1 ,6964.5  ,77.4,72.3,67.3
XS GIS Cut Line= 4
     1726969.781      112930.158     1727291.878      112936.419
     1727519.545      112848.694     1727827.514      112744.407
#Sta/Elev= 30
    10.1 1797.49    30.2 1781.46    50.3 1763.94    60.4 1756.29    70.5 1750.23
   100.7 1735.37     151 1708.68   221.5 1669.82   271.8 1640.99   322.2  1613.6
     410 1561.23   429.5 1548.25   439.3 1544.74  442.83 1544.75   448.7 1544.71
  452.39 1545.38   478.3 1551.32   497.8 1554.62   605.6 1557.14   615.4 1557.65
   625.3 1559.69   635.1  1565.5   654.8    1581   664.7 1586.54   674.5    1591
   753.3 1624.21   792.8 1640.08   822.3 1650.57   871.6 1666.54   891.3 1673.54
#Mann= 3 , 0 , 0
    10.1      .1       0  442.83    .045       0  452.39      .1       0
Bank Sta=442.83,452.39
XS Rating Curve= 0 ,0
Exp/Cntr=0.3,0.1

Type RM Length L Ch R = 1 ,6892.2  ,283.1,294.1,305.1
XS GIS Cut Line= 4
      1727038.57      113152.443     1727349.478      113020.302
     1727546.565       112879.64      1727897.25      112775.836
#Sta/Elev= 30
     9.9 1786.55    19.9 1778.26    29.8 1771.18    59.6 1753.22   129.2 1708.76
     149 1696.83   178.8  1681.4   238.5 1653.14     318 1612.39   428.6 1550.56
   438.7 1545.87   448.8  1543.1  452.08 1542.84   458.9 1542.35  460.38  1542.5
     469 1543.27   489.2 1548.69   509.3 1552.16   619.5 1556.16   629.4 1559.65
   639.3 1566.38     659 1581.54   668.9 1586.66   777.6 1630.96   807.3 1641.11
     837  1647.4   846.8 1650.15   896.3 1665.94   935.8 1677.31   945.7 1680.96
#Mann= 3 , 0 , 0
     9.9      .1       0  452.08    .045       0  460.38      .1       0
Bank Sta=452.08,460.38
XS Rating Curve= 0 ,0
Exp/Cntr=0.3,0.1

Type RM Length L Ch R = 1 ,6598.1  ,155.2,149.6,143.9
XS GIS Cut Line= 4
     1727079.046      113296.197     1727428.696      113233.369
     1727649.958       113216.98     1727934.048      113091.325
#Sta/Elev= 30
     9.9 1794.84    19.7  1786.9    39.5 1772.79    59.2 1759.74    88.8 1741.62
   177.6 1693.47   236.8  1663.6   286.2 1634.39   355.2 1591.11   405.7 1554.42
   425.8 1538.54   435.9 1532.81   437.8 1532.52     446 1531.28   447.8 1531.46
   456.1 1532.28   526.7 1545.25   546.9  1546.8   556.9 1548.19     567 1550.95
   627.2 1572.11   657.3 1580.46   697.4 1589.56   707.4 1592.76   757.5 1611.42
   787.6 1619.28   797.6 1622.76   807.6 1627.28   847.7 1649.37   887.8 1670.21
#Mann= 3 , 0 , 0
       0     .06       0   437.8    .045       0   447.8     .06       0
Bank Sta=437.8,447.8
XS Rating Curve= 0 ,0
Exp/Cntr=0.3,0.1

Type RM Length L Ch R = 1 ,6448.5  ,224.6,224.7,224.9
XS GIS Cut Line= 4
     1727100.838      113433.375     1727442.354      113405.462
     1727657.723      113327.227     1728006.654      113241.578
#Sta/Elev= 30
    10.1 1743.02    80.6 1731.82    90.7 1728.91   100.8 1724.32   151.2 1696.39
   181.4 1673.69     262 1623.02   302.3 1599.87   342.7 1579.26   422.4 1542.86
   442.3 1532.97   452.2 1529.38  458.89  1529.1   462.2 1528.98  467.97 1529.96
   531.9 1541.57   571.8 1545.89   581.8 1548.58   641.7 1569.19   651.6 1573.46
   661.6 1578.92   691.6 1597.39   701.5 1601.12   731.5 1606.64   751.4  1612.1
   771.4 1619.74   791.4 1628.71   831.3 1650.01   891.2 1684.75   931.1 1708.76
#Mann= 3 , 0 , 0
    10.1     .06       0  458.89    .045       0  467.97     .06       0
Bank Sta=458.89,467.97
XS Rating Curve= 0 ,0
Exp/Cntr=0.3,0.1

Type RM Length L Ch R = 1 ,6223.8  ,286.6,293.1,299.6
XS GIS Cut Line= 4
     1727177.385      113659.504     1727562.546      113599.408
     1727734.639      113533.849     1727996.876      113359.025
#Sta/Elev= 30
      10 1627.72      40 1623.75      90 1613.76   129.9  1603.3   209.9 1578.95
   229.9 1574.29   279.9  1564.8   379.8 1536.66   389.8 1534.52   438.3 1528.78
   461.8 1525.02   467.4 1524.14   471.8 1524.25   477.1 1524.37   506.1 1533.74
   535.2 1537.66   544.9  1541.2     574 1555.07   623.2 1584.52   642.9 1594.52
   652.8 1597.78   662.6 1599.35   682.3 1600.71     702 1604.08   731.6 1613.57
   751.3  1622.2     771 1632.58   839.9 1674.09   849.8 1678.98   889.1 1695.25
#Mann= 3 , 0 , 0
       0      .1       0   461.8    .045       0   471.8      .1       0
Bank Sta=461.8,471.8
XS Rating Curve= 0 ,0
Exp/Cntr=0.3,0.1

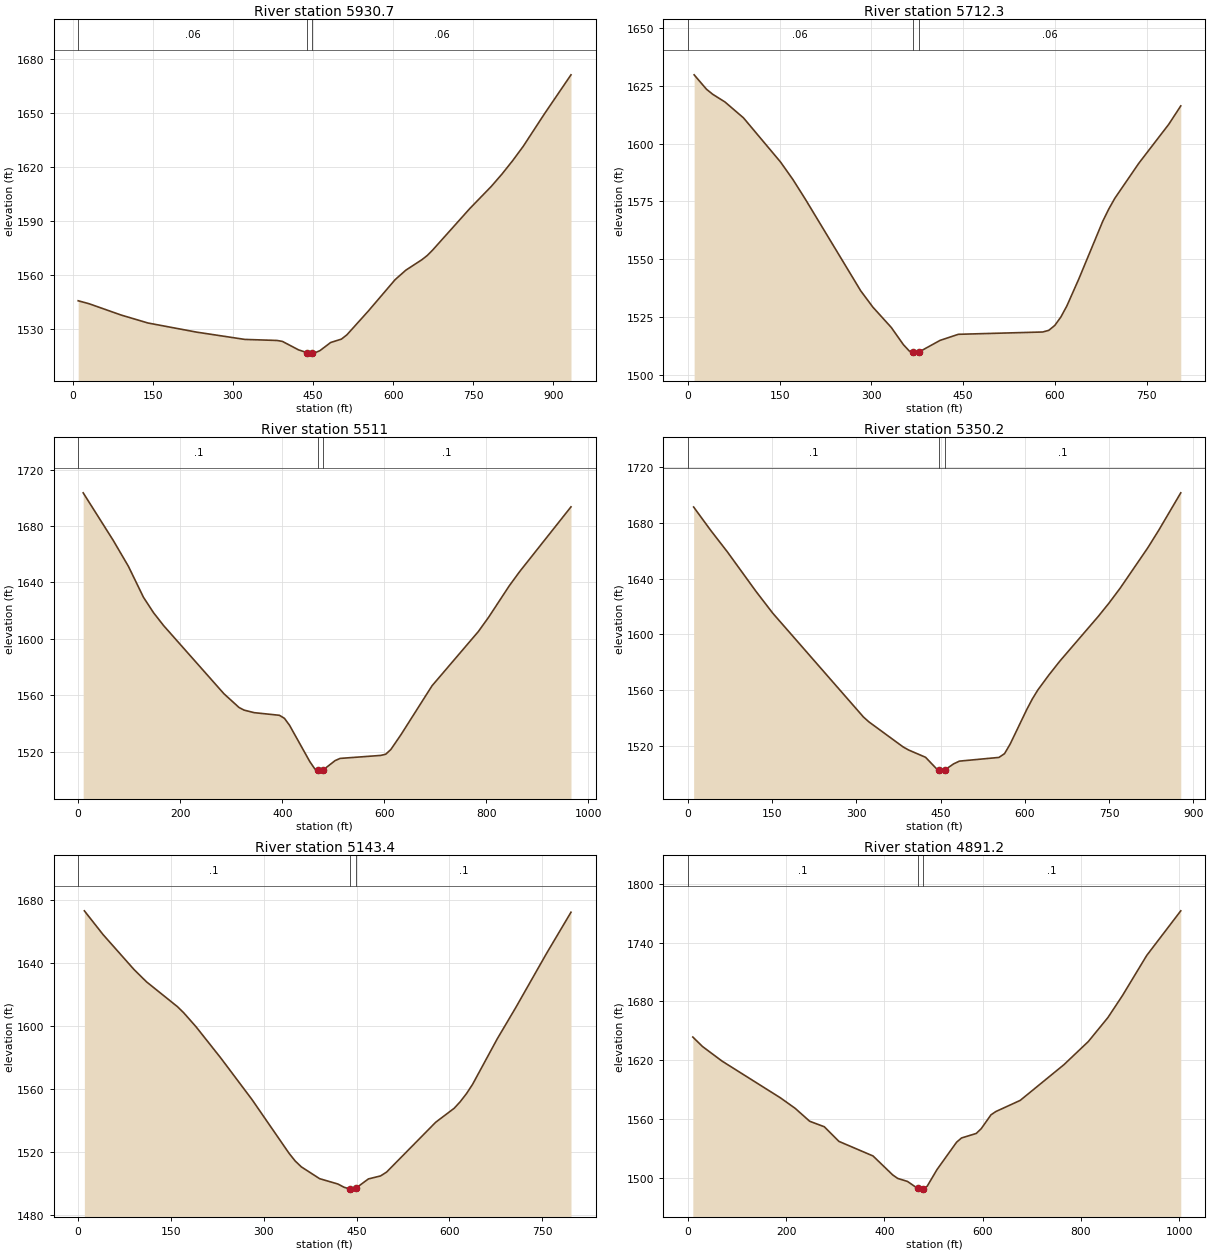
Type RM Length L Ch R = 1 ,5930.7  ,216.8,218.4,220.1
XS GIS Cut Line= 4
     1727222.411      113817.043     1727540.693      113867.109
     1727882.147       113853.45     1728134.852      113760.879
#Sta/Elev= 30
    10.1 1545.55    30.2 1543.93    90.6  1537.6     141 1533.16   231.6 1528.11
   322.2 1524.04   382.5 1523.46   392.6 1522.93   422.7 1518.24  438.48 1516.67
   442.8 1516.41  447.91 1516.46   452.9 1516.52   462.9  1517.8     483 1522.34
   503.1 1524.21   513.2 1526.55   553.4 1539.81   603.6 1557.28   623.7 1562.57
   653.9 1568.42   663.9 1570.77   673.9 1573.76   743.7 1596.94   783.5 1609.12
   803.5 1615.97   823.4 1623.39   843.3 1631.39   883.2 1649.54     933 1671.29
#Mann= 3 , 0 , 0
    10.1     .06       0  438.48    .045       0  447.91     .06       0
Bank Sta=438.48,447.91
XS Rating Curve= 0 ,0
Exp/Cntr=0.3,0.1

Type RM Length L Ch R = 1 ,5712.3  ,225.4,201.3,177.3
XS GIS Cut Line= 4
     1727283.919      114162.125     1727551.619      114071.981
     1727751.029      114080.176     1728026.923      113910.815
#Sta/Elev= 30
    10.1 1629.79    30.3 1623.56    40.4 1621.39    60.5 1618.05    90.8 1611.17
   151.3  1592.1   171.5 1584.55   191.7  1576.1   282.5 1536.36   302.4 1529.29
   332.4 1520.53   352.3 1513.06   362.3 1510.22   367.2 1509.82   372.3 1509.41
   377.2 1509.82   412.2 1514.92   442.1 1517.55   580.1 1518.55     590 1519.27
   599.8 1521.39   609.6 1524.98   619.4 1529.75     639 1541.43   678.2 1566.43
   688.1 1571.75   697.9 1576.36   737.1  1591.5   786.2 1608.41   805.8 1616.35
#Mann= 3 , 0 , 0
       0     .06       0   367.2    .045       0   377.2     .06       0
Bank Sta=367.2,377.2
XS Rating Curve= 0 ,0
Exp/Cntr=0.3,0.1

Type RM Length L Ch R = 1 ,5511    ,155.2,160.7,166.2
XS GIS Cut Line= 4
     1727599.163       114586.96     1727731.907      114279.585
     1727849.367      114050.128     1728173.838      113865.909
#Sta/Elev= 30
     9.8 1703.54    68.9 1669.68    98.5 1651.36     128 1629.41   147.7  1618.5
   167.4 1609.37   285.6 1561.03   315.1 1551.31     325 1549.43   344.7 1547.62
   394.3 1545.74   404.2 1543.58   414.1 1538.71   453.8 1512.96   463.7 1507.71
   470.6 1506.61   473.6 1506.14   480.6 1507.15   503.4 1513.59   513.3 1515.16
   592.6 1517.27   602.7 1518.13   612.8 1521.53   632.9  1532.2   693.4 1566.68
   784.2 1605.17   804.4 1615.35   844.7 1637.55   864.9 1647.57   965.7  1693.6
#Mann= 3 , 0 , 0
       0      .1       0   470.6    .045       0   480.6      .1       0
Bank Sta=470.6,480.6
XS Rating Curve= 0 ,0
Exp/Cntr=0.3,0.1

Type RM Length L Ch R = 1 ,5350.2  ,206,206.9,207.8
XS GIS Cut Line= 4
     1727649.958      114623.771     1727863.026      114317.828
     1727999.607       114170.32     1728185.358      113929.936
#Sta/Elev= 30
    10.1 1691.48    40.3 1674.83    70.5  1659.1   120.9 1631.05   151.1 1615.22
   312.4 1540.78   322.4 1537.18   382.9 1519.33   392.9 1517.05   423.1 1511.82
   443.2 1503.36   447.4 1502.73   453.2 1501.88   457.4 1502.77   473.3 1507.13
   483.4 1509.06   553.8 1511.72   563.8 1514.44   573.9 1521.41   603.3 1546.07
   613.1 1553.56   622.9 1560.03   642.5 1570.78   662.1 1580.78   730.7 1612.96
   750.2 1622.72   769.8 1633.29   818.8 1662.15   838.4 1674.82   877.6 1701.66
#Mann= 3 , 0 , 0
       0      .1       0   447.4    .045       0   457.4      .1       0
Bank Sta=447.4,457.4
XS Rating Curve= 0 ,0
Exp/Cntr=0.3,0.1

Type RM Length L Ch R = 1 ,5143.4  ,249,252.2,253.5
XS GIS Cut Line= 4
     1727729.187       114709.23     1727984.435      114482.849
      1728110.54      114358.264     1728248.799       114116.69
#Sta/Elev= 30
      10  1672.9    40.1 1657.89    90.3 1635.65   110.4 1627.87   160.6 1612.05
   170.6 1608.22   190.7 1599.27   230.8  1579.4     281 1553.16   341.2 1518.91
     351 1514.11   360.9 1510.41   390.4 1502.94     420 1499.54   429.8 1497.52
   439.2 1496.37   439.7 1496.31   449.2 1496.97   469.2 1502.78   488.9 1504.68
   498.7 1507.14   578.1 1538.76   607.9  1547.6   617.8 1551.82   627.8 1556.89
   637.7 1562.82   677.5 1591.62   707.3 1611.38     757 1645.69   796.8 1672.01
#Mann= 3 , 0 , 0
       0      .1       0   439.2    .045       0   449.2      .1       0
Bank Sta=439.2,449.2
XS Rating Curve= 0 ,0
Exp/Cntr=0.3,0.1

Type RM Length L Ch R = 1 ,4891.2  ,414.5,403,391.5
XS GIS Cut Line= 4
     1727974.141      114899.492     1728162.197      114584.645
     1728359.711      114431.192     1728386.619      114045.848
#Sta/Elev= 30
     9.9 1643.77    29.7 1634.08    69.4 1619.24   188.3 1581.78   218.1 1571.16
   247.8 1557.93   277.5 1552.35   307.3 1537.42   376.7 1522.57   416.8 1503.23
   426.8 1499.72   446.8  1496.6   467.7 1489.45   476.8 1488.77   477.7 1489.03
   486.8 1491.64   506.8  1508.6   546.8 1536.61   556.8 1540.89   586.8 1545.52
   596.8 1550.31   616.9 1564.55   626.8 1567.86   676.3 1579.21   765.4 1615.65
   814.9 1639.18   854.6 1663.49   884.3 1685.95   933.8 1726.93  1003.1  1772.4
#Mann= 3 , 0 , 0
       0      .1       0   467.7    .045       0   477.7      .1       0
Bank Sta=467.7,477.7
XS Rating Curve= 0 ,0
Exp/Cntr=0.3,0.1

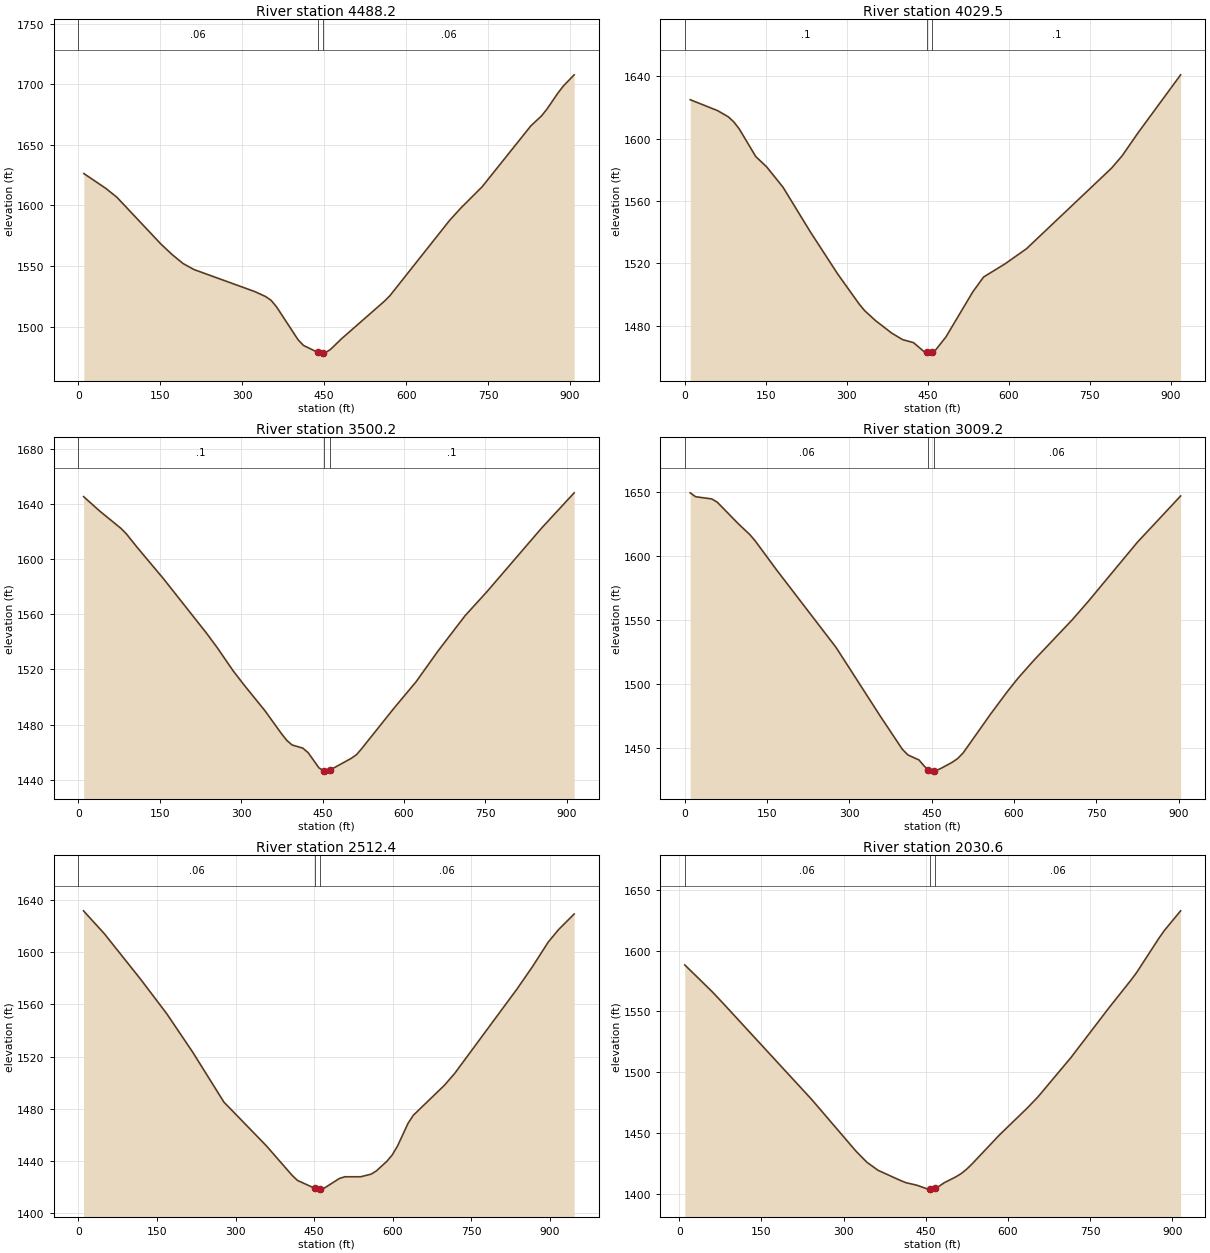
Type RM Length L Ch R = 1 ,4488.2  ,446.8,458.7,470.6
XS GIS Cut Line= 4
     1728316.477      115134.587     1728515.886      114880.545
     1728604.007       114628.17     1728742.401      114342.512
#Sta/Elev= 30
    10.1 1626.32    50.5 1614.02    70.6 1606.74   151.4 1568.01   171.6 1559.46
   191.8 1551.99   211.9 1547.01     323 1528.85   342.8 1524.76   352.7  1521.7
   362.6 1516.41   402.2 1489.13   412.1  1484.4   438.2 1478.67   441.8 1478.02
   448.2 1478.12   451.7 1478.18   461.6 1481.07   481.4 1489.71   560.6 1521.01
   570.5  1525.5   679.5 1587.54   699.4 1597.42   739.1 1615.33   828.3 1665.63
   848.2 1674.04   858.1 1679.67   877.9 1692.73   887.9 1698.59   907.7 1707.84
#Mann= 3 , 0 , 0
       0     .06       0   438.2    .045       0   448.2     .06       0
Bank Sta=438.2,448.2
XS Rating Curve= 0 ,0
Exp/Cntr=0.3,0.1

Type RM Length L Ch R = 1 ,4029.5  ,533.8,529.3,524.8
XS GIS Cut Line= 4
     1728546.939      115309.647     1728824.561      115107.271
     1729024.654        114957.7     1729251.736       114725.49
#Sta/Elev= 30
    10.1 1624.99    60.6 1618.01    80.8 1613.97    90.9 1610.71     101 1606.15
   131.4 1588.52   151.6 1581.88   181.9 1568.83   232.4 1540.22   282.9 1513.26
   323.3 1493.66   333.5 1489.44   353.5 1483.12   383.5  1475.1   403.5 1470.98
   423.5 1469.08   443.5 1463.17   448.3 1462.77   453.5 1462.33   458.3 1463.09
   463.5 1463.91   483.5 1472.68   533.4 1501.69   553.4  1511.2   593.4 1519.72
   632.7 1529.32   790.2 1581.05   809.9    1589   839.4 1603.76   918.2 1640.97
#Mann= 3 , 0 , 0
       0      .1       0   448.3    .045       0   458.3      .1       0
Bank Sta=448.3,458.3
XS Rating Curve= 0 ,0
Exp/Cntr=0.3,0.1

Type RM Length L Ch R = 1 ,3500.2  ,483.8,491,498.3
XS GIS Cut Line= 4
     1728990.398      115660.786     1729237.037      115435.067
     1729398.762      115247.179     1729640.773      115020.511
#Sta/Elev= 30
     9.8  1645.6    39.3 1635.17    78.7 1622.52    88.5 1618.57   108.2 1608.87
   157.3 1585.79     236 1546.51   255.7 1536.03   285.2 1519.11   304.8 1509.08
   344.3 1489.85     374 1473.56   383.9 1468.61   393.8 1465.17   413.7 1462.85
   423.6 1459.53   443.4 1448.53     453  1446.2   453.3 1446.13     463 1446.75
   502.9  1455.4   512.8 1458.12   522.7 1462.71   582.2 1492.09   622.4 1511.04
   662.6 1533.27   712.9 1559.14   753.1 1576.56   853.5 1622.63   913.8 1648.39
#Mann= 3 , 0 , 0
       0      .1       0     453    .045       0     463      .1       0
Bank Sta=453,463
XS Rating Curve= 0 ,0
Exp/Cntr=0.3,0.1

Type RM Length L Ch R = 1 ,3009.2  ,493.8,496.7,499.7
XS GIS Cut Line= 4
     1729198.795      115869.396       1729458.3      115812.032
     1729758.828      115648.229     1730022.202      115513.961
#Sta/Elev= 30
     9.8 1649.38    19.7 1646.34    49.2 1644.59    59.1 1642.09    98.4 1624.82
   118.1 1616.91     128 1611.97   167.3 1589.08   275.8 1528.37   356.4  1474.6
   396.6 1448.72   406.7 1444.32   426.8  1440.4   436.9 1435.36   443.6 1432.91
     447 1431.66   453.6 1431.81     457 1431.88   467.1 1433.85   487.2 1438.53
   497.3 1441.49   507.4 1445.95   557.7 1476.51   587.9  1493.9     608 1504.72
   637.6    1519   706.6 1550.27   736.1 1564.81   824.8 1610.68   903.7 1646.92
#Mann= 3 , 0 , 0
       0     .06       0   443.6    .045       0   453.6     .06       0
Bank Sta=443.6,453.6
XS Rating Curve= 0 ,0
Exp/Cntr=0.3,0.1

Type RM Length L Ch R = 1 ,2512.4  ,483,481.8,480.6
XS GIS Cut Line= 4
     1729316.543      116321.899     1729605.808      116251.825
     1729926.074      116133.697     1730187.646      115973.198
#Sta/Elev= 30
     9.9 1631.72    49.6  1614.2   119.1 1579.15   168.7 1552.86   218.3 1523.34
   277.8 1485.11   357.9 1451.99   408.1 1428.91   418.1 1425.11   450.8 1419.13
   458.3 1418.44   460.8 1418.58   468.3    1419   498.4 1426.66   508.5 1427.91
   538.6 1427.91   558.7 1429.93   568.7 1432.45   588.8 1439.83   598.8 1444.63
   608.9 1451.43   628.9  1468.8     639 1475.01   698.4 1498.03   718.2 1507.24
     837 1571.87   866.7 1589.12   896.4 1607.74   916.2 1617.34   945.9 1629.29
#Mann= 3 , 0 , 0
       0     .06       0   450.8    .045       0   460.8     .06       0
Bank Sta=450.8,460.8
XS Rating Curve= 0 ,0
Exp/Cntr=0.3,0.1

Type RM Length L Ch R = 1 ,2030.6  ,502,504,506
XS GIS Cut Line= 4
     1729497.259      116892.398     1729745.121      116718.935
     1730012.708      116601.598     1730295.747      116450.747
#Sta/Elev= 30
    10.1 1588.21    60.5 1566.01    80.7 1556.34     242 1477.49   322.7 1435.07
   342.8 1425.89     363 1419.35   403.3 1411.11   413.4 1409.24   433.5 1407.12
   453.7 1403.94  456.99  1403.9   463.7 1403.88  466.45 1404.52   473.8 1406.07
   483.9 1409.16     504 1413.73   514.1 1416.45   524.2 1420.03   534.3 1424.45
   584.6 1448.44   634.8 1470.29   654.9  1479.7     715 1511.98   785.1 1553.25
   825.2 1575.98   835.3 1582.09   875.4 1609.91   885.4 1616.36   915.4 1632.69
#Mann= 3 , 0 , 0
    10.1     .06       0  456.99    .045       0  466.45     .06       0
Bank Sta=456.99,466.45
XS Rating Curve= 0 ,0
Exp/Cntr=0.3,0.1

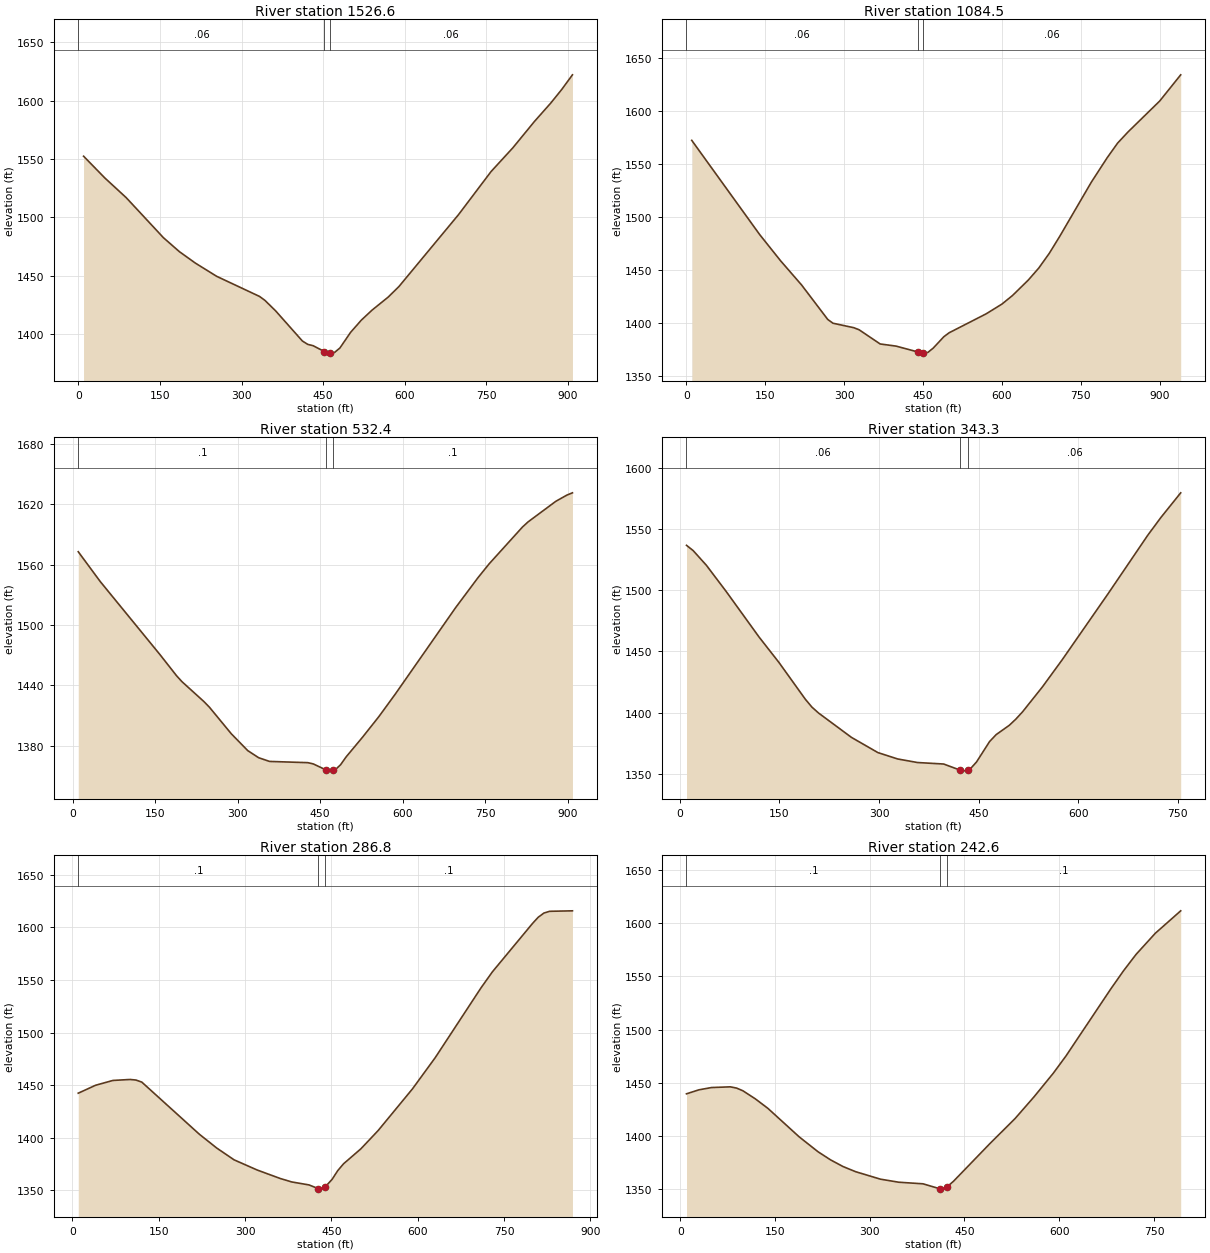
Type RM Length L Ch R = 1 ,1526.6  ,461.3,442.2,423
XS GIS Cut Line= 4
     1729717.239      117204.562     1729971.847      117134.143
      1730280.95      117034.203     1730564.612      116888.296
#Sta/Elev= 30
     9.8 1552.34    48.9 1533.68    88.1 1516.85   156.5 1482.55   185.9 1470.57
   215.2 1460.79   254.4 1449.45   333.1 1432.24   342.9  1428.9   362.6 1419.92
   411.8 1394.07   421.7 1391.18   431.5 1390.06   452.3 1385.03     461 1383.69
   462.3 1383.77   470.9 1384.28   480.7 1388.06   500.4 1401.49   520.1 1411.94
   539.8 1420.52   569.3 1431.62     589 1440.62   698.7 1502.31   758.5 1539.21
   798.4 1559.48   838.2 1582.12   868.1 1597.83   888.1 1609.38     908 1622.04
#Mann= 3 , 0 , 0
       0     .06       0   452.3    .045       0   462.3     .06       0
Bank Sta=452.3,462.3
XS Rating Curve= 0 ,0
Exp/Cntr=0.3,0.1

Type RM Length L Ch R = 1 ,1084.5  ,542.3,552,561.8
XS GIS Cut Line= 4
     1730204.358      117825.511     1730359.739       117513.84
     1730417.103      117330.821     1730677.009       117026.75
#Sta/Elev= 30
      10 1572.25   139.3 1483.37   179.1 1458.66   218.9 1435.94   268.7 1403.43
   278.6 1399.87   318.4 1395.63   328.4 1393.67   368.4 1380.31   398.7 1378.29
   440.3 1372.75   449.2 1371.68   450.3 1371.76   459.3  1372.4   469.4 1376.44
   489.6 1387.17   499.7 1390.89   570.1 1408.74   600.1 1417.93   620.1 1425.97
   650.1 1440.51   670.1 1451.86   690.1 1465.74   710.1 1481.85   770.1 1532.84
   800.1 1555.76   820.1 1569.67   840.1 1580.27   900.1  1609.3   940.1 1634.02
#Mann= 3 , 0 , 0
       0     .06       0   440.3    .045       0   450.3     .06       0
Bank Sta=440.3,450.3
XS Rating Curve= 0 ,0
Exp/Cntr=0.3,0.1

Type RM Length L Ch R = 1 ,532.4   ,191.7,189.1,186.6
XS GIS Cut Line= 4
     1730400.714      118008.266     1730692.998      117882.611
     1730932.241      117643.712     1731104.706      117458.924
#Sta/Elev= 30
     9.9 1572.83    49.7 1543.33   159.1 1470.16   188.9 1449.41   198.8 1443.49
   238.6 1423.78   248.6 1418.17   288.3 1391.81   318.2 1375.08     338    1368
   357.9 1364.29   427.5 1363.06   437.5  1361.8  461.43 1355.65   467.3 1354.64
  473.72 1355.49   477.3 1355.89   487.2 1361.04   497.1 1368.69     527  1388.3
   556.8 1408.84   586.6  1431.2   696.7 1517.42   737.1 1546.99   757.4 1560.76
     818 1597.35   828.1 1602.43   878.7 1622.96   898.9 1629.17     909 1631.41
#Mann= 3 , 0 , 0
     9.9      .1       0  461.43    .045       0  473.72      .1       0
Bank Sta=461.43,473.72
XS Rating Curve= 0 ,0
Exp/Cntr=0.3,0.1

Type RM Length L Ch R = 1 ,343.3   ,57.1,56.4,55.7
XS GIS Cut Line= 4
       1730574.9      118127.732     1730884.844      117969.721
     1730976.004      117852.732     1731091.473      117621.793
#Sta/Elev= 30
     9.9 1536.66    19.9 1532.37    39.8 1520.39    69.6 1499.01   119.3 1461.66
   149.1 1441.01   188.9 1410.92   198.8  1404.5   208.7 1399.69   258.4 1379.73
   298.2 1367.31     328  1362.1   357.8 1359.19   397.3 1357.97   421.7 1353.05
     427 1352.16  434.01 1353.36   436.9 1353.67   446.8 1359.64   466.5 1376.33
   476.4 1381.99   496.2 1389.61   506.1 1394.67   516.1 1400.58   545.9 1420.85
   575.7 1443.01   645.2 1497.27   704.8 1544.91   724.6 1559.42   754.4 1579.55
#Mann= 3 , 0 , 0
     9.9     .06       0   421.7    .045       0  434.01     .06       0
Bank Sta=421.7,434.01
XS Rating Curve= 0 ,0
Exp/Cntr=0.3,0.1

Type RM Length L Ch R = 1 ,286.8   ,43.9,44.2,44.5
XS GIS Cut Line= 4
      1730662.95      118234.992     1730887.214       118065.98
     1731039.916      117855.294     1731157.376      117549.351
#Sta/Elev= 30
      10 1442.41    40.1 1449.95    70.2 1454.53   100.3 1455.45   110.3  1454.9
   120.4 1452.96   220.6 1403.35   250.7 1390.28   280.8  1379.1   320.8 1369.46
   360.9  1361.4   380.9 1358.11   410.9 1355.28   427.1 1351.78   430.9 1351.28
  439.08 1353.39     451 1360.53     461 1368.93     471 1375.37     501 1389.53
     531 1406.88   590.7  1446.5   630.4 1476.29   709.8 1542.48   729.7 1557.78
   799.2  1603.6   809.2 1609.56   819.1 1613.55     829 1615.21   868.7 1615.67
#Mann= 3 , 0 , 0
      10      .1       0   427.1    .045       0  439.08      .1       0
Bank Sta=427.1,439.08
XS Rating Curve= 0 ,0
Exp/Cntr=0.3,0.1

Type RM Length L Ch R = 1 ,242.6   ,38,38.2,38.4
XS GIS Cut Line= 4
     1730691.989      118228.142      1730947.04      118056.534
     1731061.971      117902.244      1731180.05      117634.597
#Sta/Elev= 30
     9.9 1439.59    29.7 1443.36    49.6 1445.48    79.3 1446.15    89.2 1444.97
    99.2 1442.44     119  1434.8   138.8 1425.91   188.4  1399.1   218.2 1385.12
     238 1377.51   257.8 1371.21   277.7  1366.4     317 1359.37   345.9 1356.51
   384.4 1355.01   411.7  1350.2   413.2 1350.02   422.8 1352.34   432.5 1357.35
   490.2 1392.79   530.1 1416.35   560.3 1436.89   590.6 1458.95   610.8 1475.26
   681.4 1537.95   701.5 1554.98   721.7 1570.65     752  1590.4   792.3 1611.55
#Mann= 3 , 0 , 0
     9.9      .1       0   411.7    .045       0   422.8      .1       0
Bank Sta=411.7,422.8
XS Rating Curve= 0 ,0
Exp/Cntr=0.3,0.1