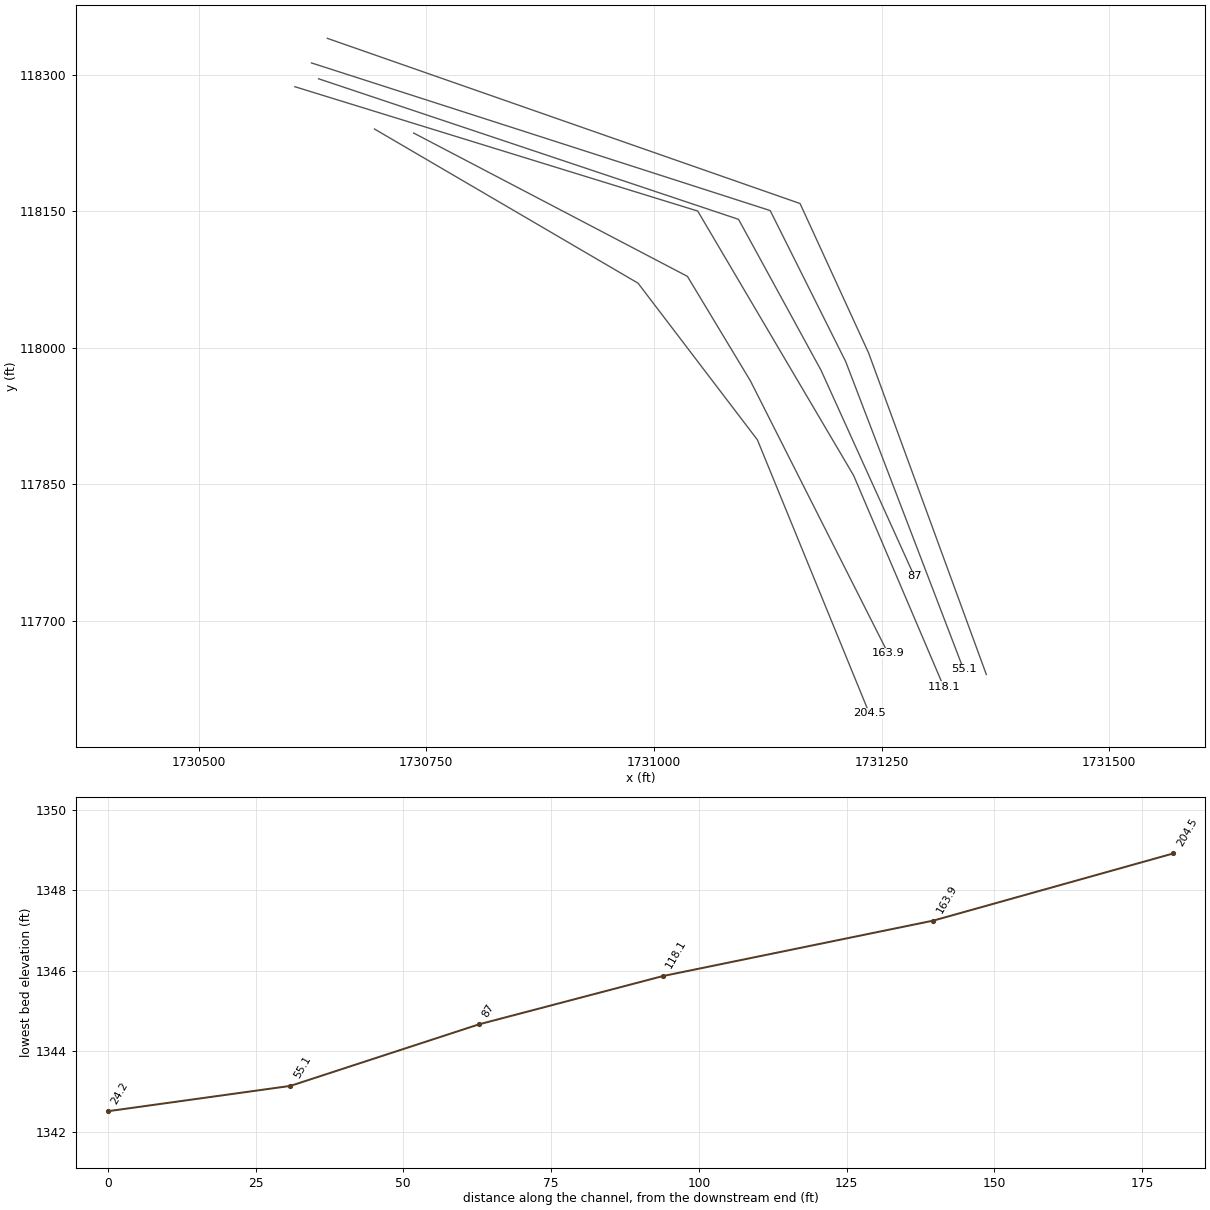
HEC-RAS study Middle Fork Bradshaw Creek.prj: Middle Fork Bradshaw Creek

--- Middle Fork Bradshaw Creek.g01 (geometry) --- (continued)

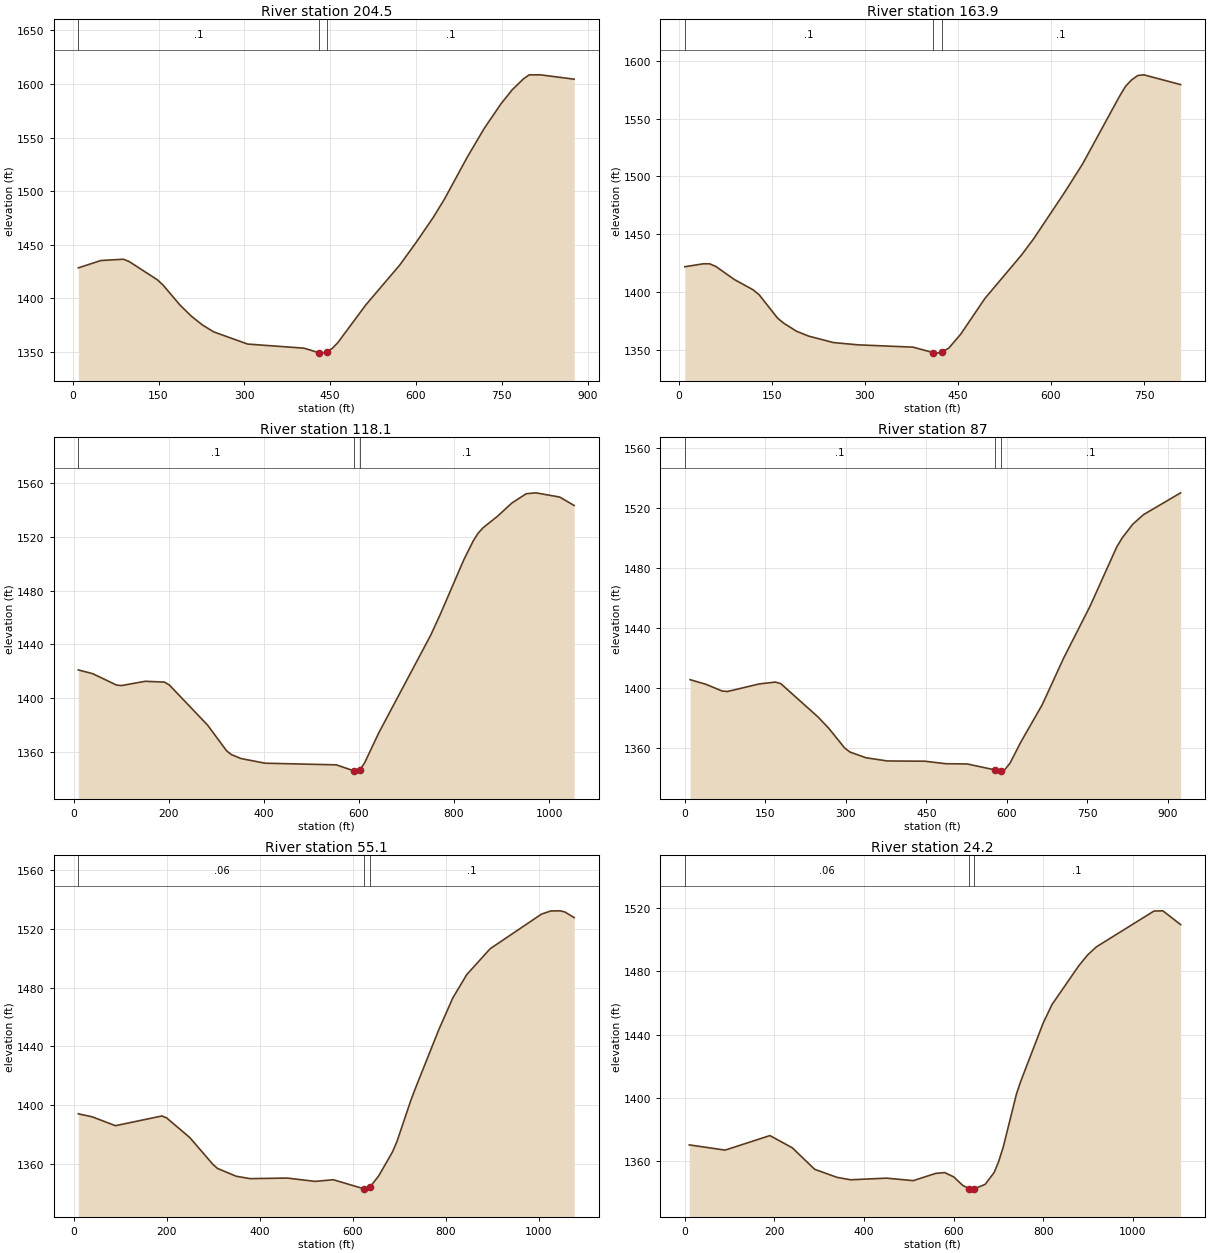
Type RM Length L Ch R = 1 ,204.5   ,42.8,40.6,38.4
XS GIS Cut Line= 4
     1730692.998      118240.455     1730982.552      118071.094
      1731113.67      117899.001     1731236.594      117598.521
#Sta/Elev= 30
     9.9 1428.49    49.3 1435.34    88.8 1436.54    98.7 1434.38     148 1417.38
   157.9 1412.49   187.5 1393.84   207.2 1383.51   226.9 1375.14   246.7 1368.68
   305.8 1357.38   404.3 1353.54   431.1 1349.16   433.8 1348.92   443.6 1350.08
   453.5 1353.27   463.3 1358.66   512.5 1394.06   571.5 1431.06     601 1452.81
   630.5 1475.86   650.2 1493.05   689.5 1531.71     719 1558.42   748.6 1581.63
   768.2 1594.71   787.9 1604.88   797.7 1608.56   817.4 1608.62   876.4 1604.57
#Mann= 3 , 0 , 0
     9.9      .1       0   431.1    .045       0   443.6      .1       0
Bank Sta=431.1,443.6
XS Rating Curve= 0 ,0
Exp/Cntr=0.3,0.1

Type RM Length L Ch R = 1 ,163.9   ,46,45.8,45.6
XS GIS Cut Line= 4
     1730736.072      118236.014     1731036.781      118078.575
     1731106.054      117963.645     1731257.195      117664.511
#Sta/Elev= 30
      10 1421.91    39.9 1424.48    49.9 1424.46    59.9  1422.2    89.8  1410.9
   119.8 1402.06   129.8 1397.69   159.7 1377.36   169.7 1373.03   189.7 1366.24
   209.6 1361.95   249.6 1356.36   289.5  1354.4   377.8 1352.42     410  1347.7
   416.1 1347.25   423.8 1348.08   435.3 1351.58   454.5  1363.6   493.3 1394.38
   552.5 1432.08   572.2 1446.22   621.5 1485.87   651.1 1510.99   710.2 1569.11
   720.1 1577.89   729.9 1583.46   739.8  1587.2   749.6  1587.8   808.8 1579.35
#Mann= 3 , 0 , 0
      10      .1       0     410    .045       0   423.8      .1       0
Bank Sta=410,423.8
XS Rating Curve= 0 ,0
Exp/Cntr=0.3,0.1

Type RM Length L Ch R = 1 ,118.1   ,31.7,31.1,30.4
XS GIS Cut Line= 4
     1730605.586      118286.893     1731048.111      118150.311
      1731219.41      117859.735     1731318.363      117627.643
#Sta/Elev= 30
    10.1 1421.06    40.3 1418.28    90.6 1409.78   100.7 1409.45     151 1412.61
   191.3    1412   201.4  1409.9   281.9 1380.06   322.2 1360.83   332.2  1358.1
   352.4 1355.21   402.7 1351.76   552.4 1350.54  589.13 1346.16   592.1 1345.87
     602 1346.84   611.9 1351.88   641.7  1374.2   750.8  1446.7   770.7 1461.96
   820.6 1502.83   840.8 1517.12   850.9 1522.67     861 1526.62   891.3 1535.16
   921.5 1544.99   951.8 1551.95     972 1552.63  1022.5 1549.47  1052.7 1543.22
#Mann= 3 , 0 , 0
    10.1      .1       0  589.13    .045       0     602      .1       0
Bank Sta=589.13,602
XS Rating Curve= 0 ,0
Exp/Cntr=0.3,0.1

Type RM Length L Ch R = 1 ,87      ,32.6,31.9,31.2
XS GIS Cut Line= 4
     1730631.576      118295.638      1731092.95      118141.204
      1731183.68      117975.186     1731285.993      117749.326
#Sta/Elev= 30
     9.9 1405.68    39.7 1402.55    69.5 1398.12    79.4 1397.79     139 1402.85
   168.8 1404.08   178.7 1403.07   248.2 1380.81   268.1  1373.3   297.9 1360.09
   307.8 1357.38   337.6 1353.59   377.3 1351.45   446.8 1351.29   486.5 1349.62
   526.4 1349.44   578.2 1345.46   586.1 1344.67   588.2 1344.87   596.1 1345.63
     606 1350.06   625.9 1363.99   665.8 1388.92   705.5 1419.87   755.1 1454.81
   804.7 1494.23   814.6 1500.14   834.4 1509.33   854.3 1515.72   923.7 1530.33
#Mann= 3 , 0 , 0
       0      .1       0   578.2    .045       0   588.2      .1       0
Bank Sta=578.2,588.2
XS Rating Curve= 0 ,0
Exp/Cntr=0.3,0.1

Type RM Length L Ch R = 1 ,55.1    ,31.4,30.9,30.5
XS GIS Cut Line= 4
     1730623.855      118313.012     1731127.698      118150.856
     1731210.706      117984.838     1731340.045      117647.013
#Sta/Elev= 30
      10 1394.28    39.9 1392.24    89.9 1386.22   189.7 1392.81   199.7 1391.56
   249.7 1378.19   299.6 1359.92   309.6 1357.15   349.5  1351.9   379.5 1350.26
   459.4 1350.65   519.3 1348.39   558.6 1349.52   625.4 1343.25     627 1343.14
   636.8 1344.34   656.3 1352.21   685.6 1368.29   695.4 1375.46     725 1403.17
     735 1411.52   785.2 1451.25   815.4 1472.86   845.5 1488.78   895.8 1506.35
  1006.3 1529.89  1026.4 1532.04  1046.5 1532.12  1056.5 1531.34  1076.6 1527.53
#Mann= 3 , 0 , 0
      10     .06       0   625.4    .045       0   636.8      .1       0
Bank Sta=625.4,636.8
XS Rating Curve= 0 ,0
Exp/Cntr=0.3,0.1

Type RM Length L Ch R = 1 ,24.2    ,31.7,24.2,16.7
XS GIS Cut Line= 4
     1730641.229      118340.038     1731160.515      118158.577
     1731235.802      117994.491     1731365.141      117641.221
#Sta/Elev= 30
      10  1370.4      90 1367.11     190 1376.27     240 1368.57     290    1355
     340 1349.92   370.1  1348.4   450.1 1349.43   510.1 1347.87   560.1 1352.43
   580.2 1352.94   600.2 1350.25   620.3 1344.89   634.9 1342.81   640.3 1342.51
   644.9 1342.58   670.4  1345.5   690.5 1352.99   700.5  1359.8   710.6 1368.79
   740.5 1402.65   750.4 1410.87   799.9 1447.16   819.7 1458.89   879.1 1483.21
   898.9 1490.07   918.7 1495.25  1047.4 1517.85  1067.2 1517.98  1106.8 1509.28
#Mann= 3 , 0 , 0
       0     .06       0   634.9    .045       0   644.9      .1       0
Bank Sta=634.9,644.9
XS Rating Curve= 0 ,0
Exp/Cntr=0.3,0.1

Chan Stop Cuts=-1
Use User Specified Reach Order=0